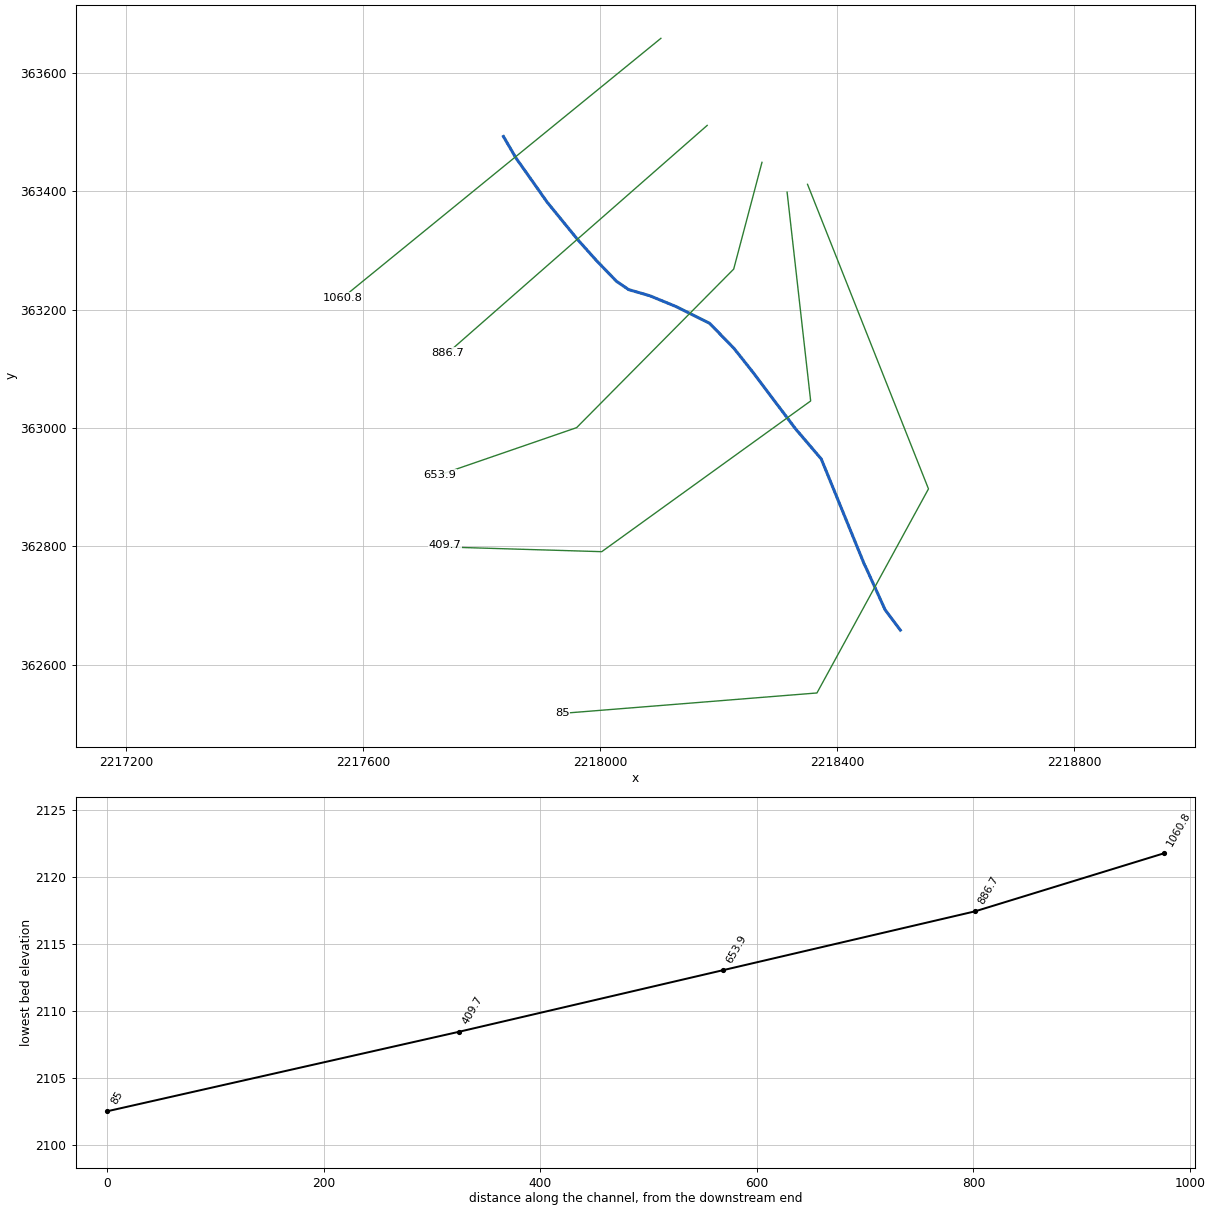
--- TwomileRun.prj (project) ---

Proj Title=TwomileRun
Current Plan=p01
Geom File=g01
Flow File=f01
Plan File=p01
DSS Export Rating Curves=0
DSS Export Rating Curve Sorted=0
DSS Export Volume Flow Curves=0
DXF OffsetX=0
DXF OffsetY=0
DXF ScaleX=0
DXF ScaleY=0

--- TwomileRun.p01 (plan) ---

Plan Title=Floodplain
Program Version=4.00
Geom File=g01
Flow File=f01
K Sum by GR=0
Std Step Tol=0.01
Critical Tol=0.01
Num of Std Step Trials=20
Max Error Tol=0.3
Flow Tol Ratio=0.001
Split Flow NTrial=30
Split Flow Tol=0.02
Split Flow Ratio=0.02
Log Output Level=0
Friction Slope Method=1
Unsteady Friction Slope Method=2
Unsteady Bridges Friction Slope Method=1
Global Log Level=0
CheckData=False
Run HTab=0
Run UNet=0
Run PostProcess=0
UNET Theta=0
UNET Theta Warmup=0
UNET ZTol=0
UNET ZSATol=0
UNET MxIter=0
UNET MaxInSteps=0
UNET DtIC=0
UNET DtMin=0
UNET MaxCRTS=0
UNET WFStab=0
UNET SFStab=0
UNET WFX=0
UNET SFX=0
UNET DSS MLevel=0
UNET DZMax Abort=0
UNET Convert EG Bridges=0
UNET Use Existing IB Tables=0
UNET Froude Limit=0
UNET Froude Power=0
Write IC File=0
Echo Input=False
Echo Output=False
Write Detailed=0

--- TwomileRun.f01 (steady flow) ---

Flow Title=NFF Regression Equation
Program Version=4.00
Number of Profiles=1
Profile Names=P100yr
River Rch & RM=TwomileRun,Main      ,1060.8
598.3089
Boundary for River Rch & Prof#=TwomileRun,Main      ,1
Up Type=0
Dn Type=3
Dn Slope=0.018535

--- TwomileRun.g01 (geometry) ---

Geom Title=USGS 10m DEM
Program Version=4.10

River Reach=TwomileRun      ,Main
Reach XY= 20
     2217837.283      363492.183     2217858.598      363455.617
     2217883.037      363421.072     2217910.967      363381.382
     2217962.049      363318.724     2217994.388      363282.526
     2218028.198      363247.613     2218048.594      363233.648
     2218084.058      363223.359     2218128.708      363204.984
     2218185.303      363176.686     2218219.369      363141.556
     2218226.463      363134.241      2218256.23      363096.756
     2218330.431      362998.292     2218373.577      362947.766
     2218447.014      362768.078      2218448.49      362765.548
     2218481.376      362692.975     2218507.074      362658.567

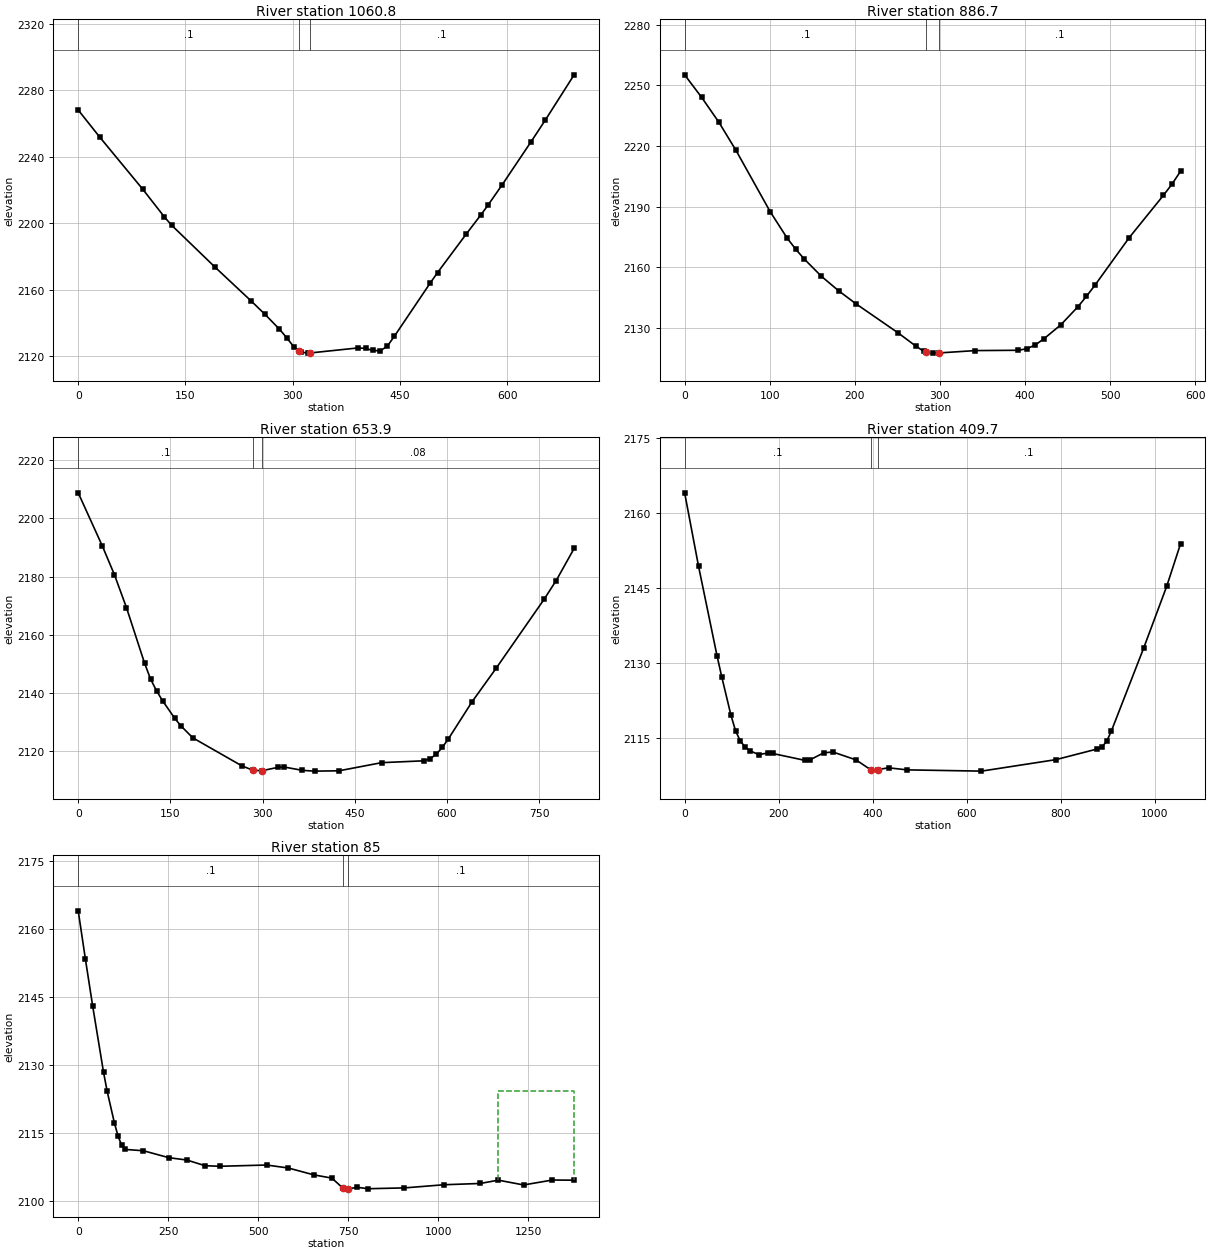
Type RM Length L Ch R = 1 ,1060.8  ,173.4,174.1,175
XS GIS Cut Line= 2
     2218103.001      363657.966     2217565.639       363219.76
#Sta/Elev= 30
       0 2268.15    30.2 2251.79    90.4 2220.36   120.6 2203.71   130.6 2198.78
   190.9 2173.69   241.2  2153.4   261.3 2145.04   281.4 2136.16   291.4 2131.06
   301.5 2125.53   309.4 2123.03   311.5 2122.36   321.6 2121.74   324.4 2121.85
   391.9  2124.9     402 2124.55     412 2123.35   422.1  2123.1   432.1 2125.86
   442.2 2131.97   492.4 2164.08   502.4 2170.23   542.6 2193.48   562.8 2204.86
   572.8 2210.73   592.9 2223.18   633.1 2248.98   653.2 2262.14   693.4 2289.35
#Mann= 3 , 0 , 0
       0      .1       0   309.4    .045       0   324.4      .1       0
Bank Sta=309.4,324.4
XS Rating Curve= 0 ,0
Exp/Cntr=0.3,0.1

Type RM Length L Ch R = 1 ,886.7   ,231.4,232.8,234.2
XS GIS Cut Line= 2
     2218181.123      363510.939     2217742.974      363126.509
#Sta/Elev= 30
       0 2255.28    20.1 2244.05    40.2 2231.84    60.3  2217.9   100.5 2187.54
   120.6 2174.33   130.6 2168.89   140.7 2164.01   160.8 2155.48   180.9 2148.35
     201 2141.98   251.2 2127.38   271.4 2121.02   281.4 2118.24   283.9 2118.04
   291.4 2117.43   298.9 2117.52   341.7 2118.69   391.9 2118.84     402 2119.57
     412 2121.44   422.1 2124.45   442.2 2131.46   462.3 2140.41   472.3 2145.57
   482.4 2151.13   522.6 2174.65   562.8  2195.6   572.8  2201.1   582.9  2207.5
#Mann= 3 , 0 , 0
       0      .1       0   283.9    .045       0   298.9      .1       0
Bank Sta=283.9,298.9
XS Rating Curve= 0 ,0
Exp/Cntr=0.3,0.1

Type RM Length L Ch R = 1 ,653.9   ,247.8,244.2,240.7
XS GIS Cut Line= 4
     2218273.574      363448.568     2218225.856      363268.301
     2217960.758      363000.552     2217730.122      362921.022
#Sta/Elev= 30
       0  2208.8    39.3 2190.49    58.9 2180.65    78.5 2169.33     108  2150.2
   117.8 2144.71   127.6 2140.65   137.4 2137.23     157 2131.27   166.8  2128.7
   186.5 2124.51   265.8 2114.93   284.3 2113.35   299.3  2113.2   325.3 2114.36
   335.2 2114.47     365 2113.31   384.8 2113.05   424.4 2113.16   493.8 2115.96
   563.3 2116.61     573 2117.33   582.8 2118.86   592.5 2121.18   602.3 2124.07
   641.3 2136.98   680.4 2148.48   758.4 2172.18     778 2178.62   807.2 2189.65
#Mann= 3 , 0 , 0
       0      .1       0   284.3    .045       0   299.3     .08       0
Bank Sta=284.3,299.3
XS Rating Curve= 0 ,0
Exp/Cntr=0.3,0.1

Type RM Length L Ch R = 1 ,409.7   ,312.2,324.6,337
XS GIS Cut Line= 5
      2218315.99      363398.199     2218355.754      363045.618
     2218003.174      362791.124     2217738.075      362799.077
     2217738.075      362801.728
#Sta/Elev= 30
       0 2164.01    29.6 2149.35      69 2131.44    78.8 2127.34    98.6 2119.59
   108.4 2116.49   118.3  2114.5   128.1 2113.33     138 2112.56   157.7 2111.76
   177.4 2112.08   187.3 2111.98   256.3  2110.6   266.1 2110.68   295.7 2112.11
   315.4 2112.28   364.7  2110.7     396 2108.72     411 2108.78   433.9 2109.12
   473.4 2108.71   631.5 2108.46   789.6 2110.75   878.1 2112.89   887.9 2113.32
   897.7  2114.4   907.5  2116.4   976.3 2132.98  1025.4 2145.33  1054.9 2153.83
#Mann= 3 , 0 , 0
       0      .1       0     396    .045       0     411      .1       0
Bank Sta=396,411
XS Rating Curve= 0 ,0
Exp/Cntr=0.3,0.1

Type RM Length L Ch R = 1 ,85      ,97.1,85,73
XS GIS Cut Line= 4
     2218350.453      363411.454     2218554.578      362897.163
     2218366.358      362552.535     2217936.899      362518.072
#Sta/Elev= 30
       0 2163.97    20.1 2153.24    40.2 2142.94    70.4 2128.29    80.5  2124.1
   100.6 2117.12   110.7 2114.23   120.7 2112.22   130.8 2111.31   181.1 2111.02
   251.5 2109.49   301.8 2108.97   352.1 2107.72   392.4 2107.59   523.1 2107.87
   583.5 2107.21     654  2105.7   704.4 2104.98   734.8 2102.77   744.6 2102.55
   749.8 2102.62   774.8 2102.95     805 2102.64   905.7 2102.82  1016.1 2103.52
  1116.3  2103.8  1166.4 2104.53  1236.6 2103.47  1316.7 2104.56  1376.8 2104.52
#Mann= 3 , 0 , 0
       0      .1       0   734.8    .045       0   749.8      .1       0
#XS Ineff= 2 , 0
                         1165.26         2124.11
Permanent Ineff=
       F       F
Bank Sta=734.8,749.8
XS Rating Curve= 0 ,0
Exp/Cntr=0.3,0.1

Chan Stop Cuts=-1
Use User Specified Reach Order=0
Composite Channel Slope=5